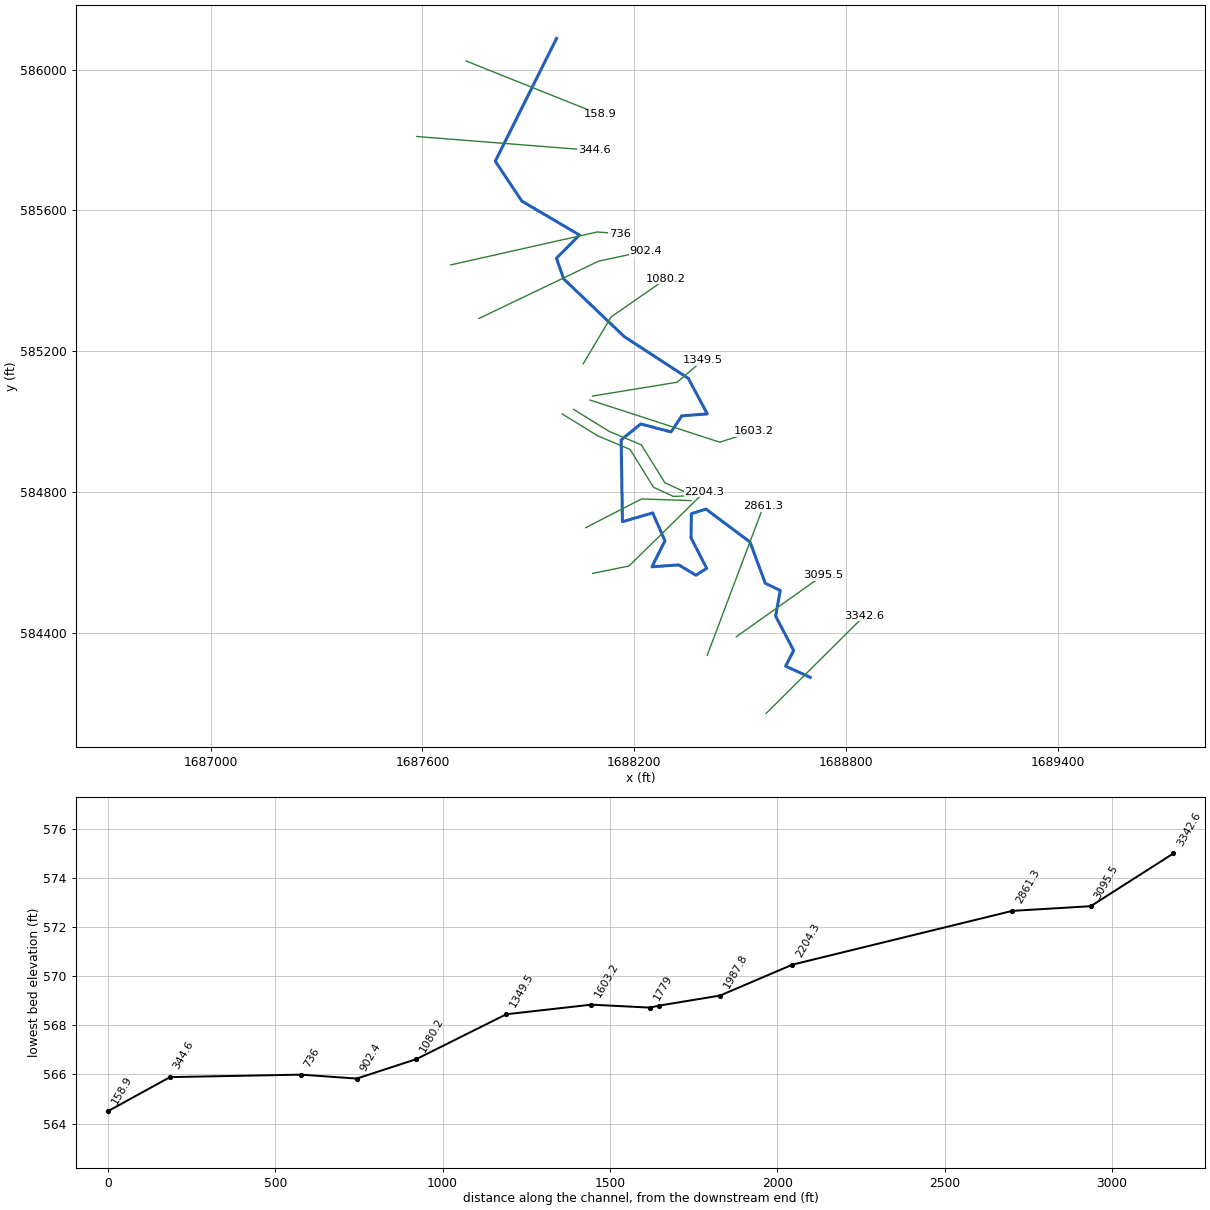
--- CrossCr.prj (project) ---

Proj Title=CrossCr
Current Plan=p01
Default Exp/Contr=0,0
English Units
Geom File=g01
Flow File=f01
Plan File=p01
BEGIN DESCRIPTION:
AMEC Environment & Infrastructure, 2013
Projection: NAD 1983 State Plane West Virginia South FIPS 4702 (US Feet)
Vertical Datum: NAVD 1988
END DESCRIPTION:
DSS Export Rating Curves= 0
DSS Export Rating Curve Sorted= 0
DSS Export Volume Flow Curves= 0
DXF OffsetX= 0
DXF OffsetY= 0
DXF ScaleX= 0
DXF ScaleY= 0

--- CrossCr.p01 (plan) ---

Plan Title=Floodplain
Program Version=4.00
Geom File=g01
Flow File=f01
K Sum by GR=0
Std Step Tol=0.01
Critical Tol=0.01
Num of Std Step Trials=20
Max Error Tol=0.3
Flow Tol Ratio=0.001
Split Flow NTrial=30
Split Flow Tol=0.02
Split Flow Ratio=0.02
Log Output Level=0
Friction Slope Method=1
Unsteady Friction Slope Method=2
Unsteady Bridges Friction Slope Method=1
Global Log Level=0
CheckData=False
Run HTab=0
Run UNet=0
Run PostProcess=0
UNET Theta=0
UNET Theta Warmup=0
UNET ZTol=0
UNET ZSATol=0
UNET MxIter=0
UNET MaxInSteps=0
UNET DtIC=0
UNET DtMin=0
UNET MaxCRTS=0
UNET WFStab=0
UNET SFStab=0
UNET WFX=0
UNET SFX=0
UNET DSS MLevel=0
UNET DZMax Abort=0
UNET Convert EG Bridges=0
UNET Use Existing IB Tables=0
UNET Froude Limit=0
UNET Froude Power=0
Write IC File=0
Echo Input=False
Echo Output=False
Write Detailed=0

--- CrossCr.f01 (steady flow) ---

Flow Title=USGS Regress. Eqn. (2010) - Western-Plateaus
Program Version=4.10
Number of Profiles= 1
Profile Names=P100yr
River Rch & RM=CrossCr,Main            ,3342.6
     723
River Rch & RM=CrossCr,Main            ,3095.5
     723
River Rch & RM=CrossCr,Main            ,2861.3
     904
River Rch & RM=CrossCr,Main            ,1987.8
     907
River Rch & RM=CrossCr,Main            ,1779
     909
Boundary for River Rch & Prof#=CrossCr,Main            , 1
Up Type= 0
Dn Type= 3
Dn Slope=0.00154
DSS Import GetInterval= 0
DSS Import GetPeak= 0
DSS Import FillOption= 0

--- CrossCr.g01 (geometry) ---

Geom Title=USGS 3m DEM
Program Version=4.10

River Reach=CrossCr         ,Main
Reach XY= 30
     1688698.832      584274.272     1688629.123      584306.049
     1688651.909      584350.537     1688600.911      584448.193
     1688613.932      584520.893     1688571.614      584541.509
     1688528.212      584658.696     1688403.429      584752.012
     1688362.196      584738.991     1688361.111      584670.632
     1688405.599      584583.827     1688375.217      584564.295
     1688326.389      584593.592     1688250.434      584588.167
     1688287.326      584661.952     1688252.604      584741.162
     1688166.883      584716.205     1688163.268      584948.323
     1688218.639        584993.7     1688304.687      584971.196
     1688335.069      585016.769     1688407.357       585022.26
     1688353.504      585123.234     1688172.003      585241.747
     1688000.408      585405.616     1687979.937      585464.181
     1688045.052      585530.177     1687881.805       585626.54
     1687806.601      585739.554     1687980.223      586088.621

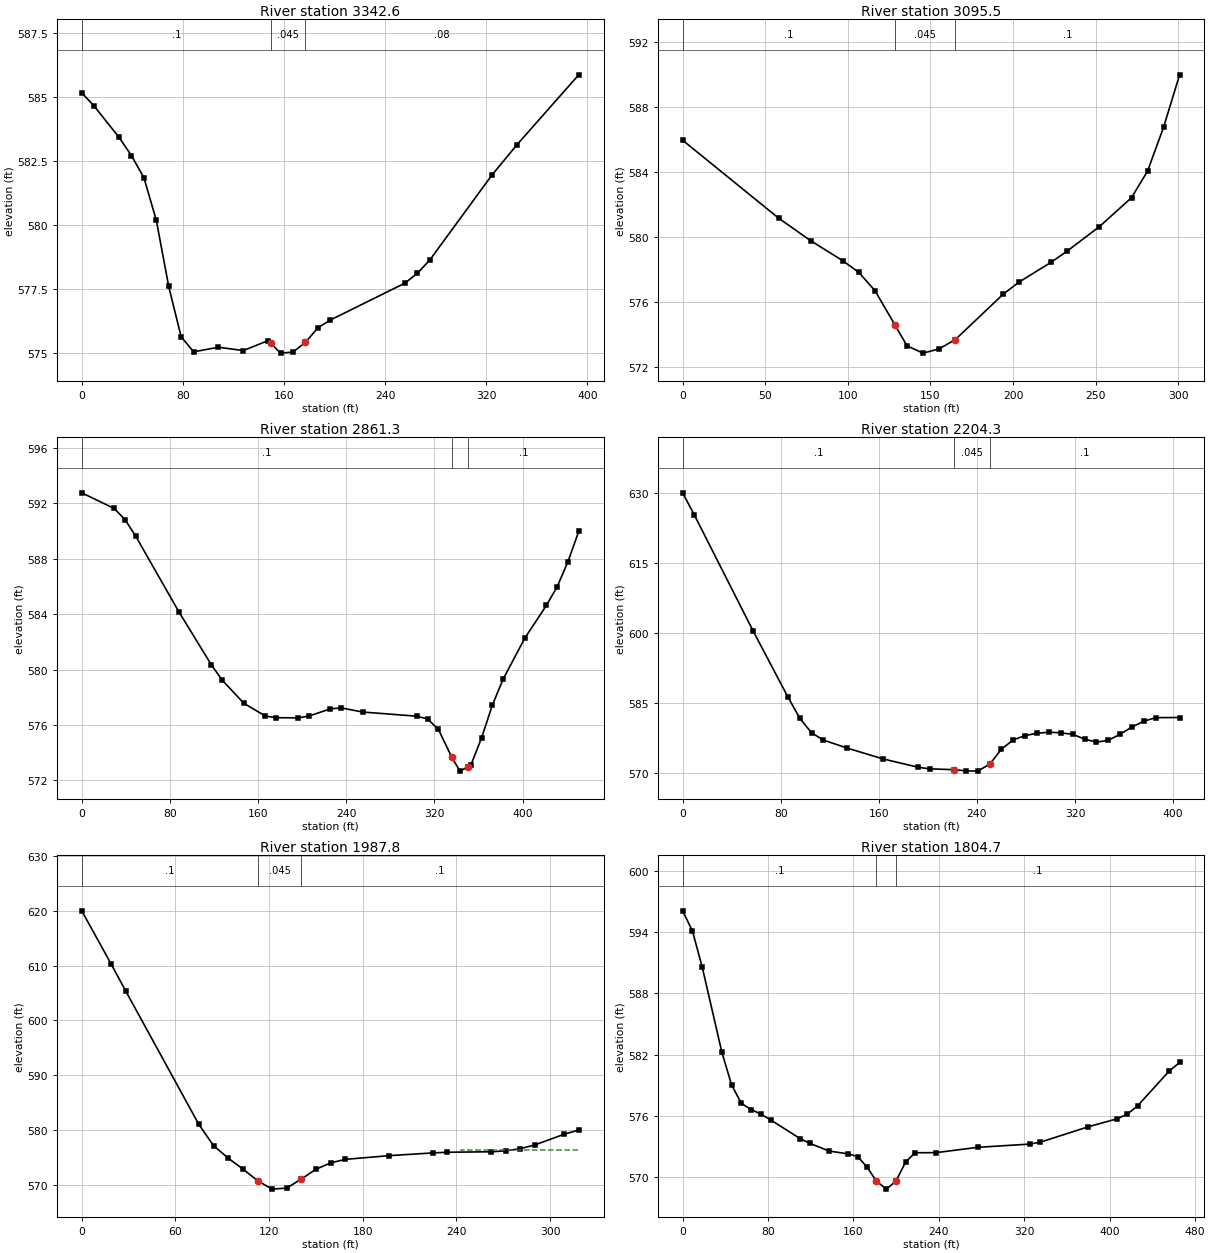
Type RM Length L Ch R = 1 ,3342.6  ,247.9,247.1,248.8
XS GIS Cut Line= 2
     1688574.043      584172.002     1688852.734      584449.446
#Sta/Elev= 24
       0  585.16     9.8  584.64    29.5  583.42    39.3  582.71    49.2  581.84
      59  580.18    68.8   577.6    78.6  575.64    88.5  575.05   108.1  575.23
   127.8   575.1   147.5  575.49   149.6  575.38   157.3     575   167.1  575.04
     177  575.42   186.8  575.99   196.6  576.29   255.6  577.73   265.4  578.11
   275.3  578.63   324.4  581.94   344.1  583.12   393.2  585.86
#Mann= 3 , 0 , 0
       0      .1       0   149.6    .045       0     177     .08       0
Bank Sta=149.6,177
XS Rating Curve= 0 ,0
Exp/Cntr=0.3,0.1

Type RM Length L Ch R = 1 ,3095.5  ,217,234.2,239.3
XS GIS Cut Line= 2
     1688489.364      584389.499     1688734.485      584563.831
#Sta/Elev= 20
       0  585.97    58.2  581.16    77.6  579.77      97  578.54   106.7  577.82
   116.4   576.7   128.5  574.59   135.8   573.3   145.5  572.85   155.2  573.11
     165  573.68   194.1  576.49   203.8  577.24   223.2  578.46   232.9  579.15
   252.3  580.65   271.7  582.43   281.4  584.07   291.1  586.77   300.8     590
#Mann= 3 , 0 , 0
       0      .1       0   128.5    .045       0     165      .1       0
Bank Sta=128.5,165
XS Rating Curve= 0 ,0
Exp/Cntr=0.3,0.1

Type RM Length L Ch R = 1 ,2861.3  ,670.1,657,204.6
XS GIS Cut Line= 2
     1688407.316      584337.394      1688566.04      584759.559
#Sta/Elev= 30
       0  592.77    29.4  591.64    39.2  590.84      49  589.63    88.2  584.16
   117.7  580.33   127.5  579.23   147.1  577.56   166.7  576.64   176.5  576.52
   196.1  576.51   205.9  576.63   225.5  577.16   235.3  577.23   254.9  576.93
     304  576.63   313.8  576.43   323.6  575.68   335.8  573.66   343.2  572.66
   350.8  572.98     353  573.07   362.8  575.06   372.6  577.43   382.4  579.31
     402  582.26   421.6  584.63   431.4  585.98   441.2  587.79     451  589.99
#Mann= 3 , 0 , 0
       0      .1       0   335.8    .045       0   350.8      .1       0
Bank Sta=335.8,350.8
XS Rating Curve= 0 ,0
Exp/Cntr=0.3,0.1

Type RM Length L Ch R = 1 ,2204.3  ,216.6,216.6,611.9
XS GIS Cut Line= 3
      1688082.53      584569.395     1688185.487      584590.441
     1688399.456      584801.056
#Sta/Elev= 30
       0     630     9.6  625.24    57.3  600.55      86  586.26    95.5  581.81
   105.1  578.67   114.8  577.11   134.1  575.41   163.2   573.1   192.2  571.29
   201.9  570.95   221.3  570.78     231  570.53   240.7  570.47   250.7  572.01
     260  575.17   269.7  577.16   279.4  578.09   289.1  578.56   298.8   578.8
   308.5  578.65   318.2  578.34   327.8  577.32   337.5  576.67   347.2  577.06
   356.9  578.38   366.6  579.93   376.3  581.17     386  581.91   405.3  581.94
#Mann= 3 , 0 , 0
       0      .1       0   221.3    .045       0   250.7      .1       0
Bank Sta=221.3,250.7
XS Rating Curve= 0 ,0
Exp/Cntr=0.3,0.1

Type RM Length L Ch R = 1 ,1987.8  ,208.3,183,158.5
XS GIS Cut Line= 3
     1688062.791      584699.222     1688221.199      584780.894
      1688361.32      584776.087
#Sta/Elev= 23
       0     620    18.8   610.3    28.1   605.4      75  581.02    84.4  577.15
    93.8  574.87   103.2  572.88   112.6  570.76   121.9  569.21   131.3   569.4
   140.7  571.06   150.1  572.85   159.5     574   168.8  574.64   196.9  575.32
     225  575.82   234.3  575.94   262.4  576.03   271.7   576.2     281  576.59
   290.4  577.29   309.1  579.23   318.4     580
#Mann= 3 , 0 , 0
       0      .1       0   112.6    .045       0   140.7      .1       0
#XS Ineff= 2 , 0
                          243.03          576.39
Permanent Ineff=
       F       F
Bank Sta=112.6,140.7
XS Rating Curve= 0 ,0
Exp/Cntr=0.3,0.1

Type RM Length L Ch R = 1 ,1804.7  ,25.9,25.7,25.9
XS GIS Cut Line= 6
     1687996.069      585022.341     1688097.427      584959.693
     1688188.427      584921.498     1688255.122      584813.837
     1688311.524      584787.942     1688370.369      584790.634
#Sta/Elev= 30
       0  596.11     9.2  594.13    18.3  590.61    36.7  582.26    45.8  579.04
      55  577.22    64.2  576.61    73.3  576.16    82.5  575.59     110  573.76
   119.2  573.29   137.1  572.54     155  572.26     164     572     173  570.93
   181.5  569.58   190.9   568.8   199.9   569.6   208.9  571.47   217.8  572.37
   237.3  572.38   276.3   572.9     325  573.22   334.8   573.4     380  574.92
   406.6  575.69   416.4  576.15   426.2  576.98   455.6  580.37   465.5  581.23
#Mann= 3 , 0 , 0
       0      .1       0   181.5    .045       0   199.9      .1       0
Bank Sta=181.5,199.9
XS Rating Curve= 0 ,0
Exp/Cntr=0.3,0.1

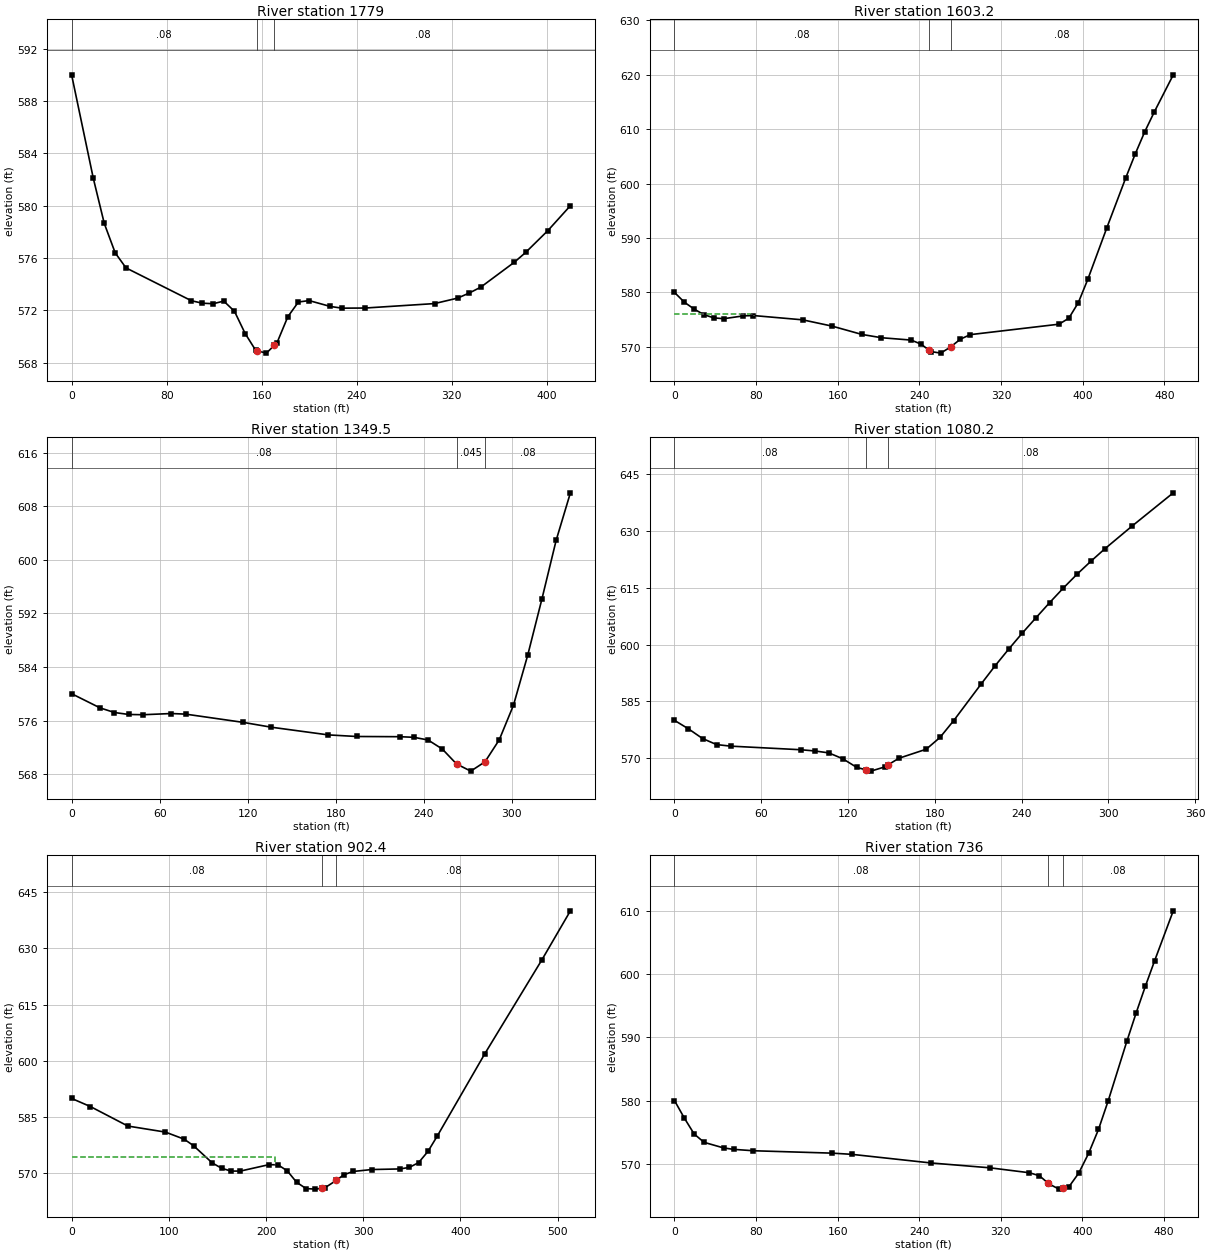
Type RM Length L Ch R = 1 ,1779    ,85.4,175.8,178.8
XS GIS Cut Line= 5
     1688028.131      585035.249      1688129.49      584972.602
      1688220.49      584934.407     1688287.184      584826.746
     1688355.706      584795.287
#Sta/Elev= 30
       0  590.01    18.3  582.08    27.5  578.64    36.7  576.39    45.8  575.24
   100.8  572.73     110  572.54   119.2   572.5   128.1   572.7   137.1  571.92
   146.1  570.22     155  568.93   155.8  568.91     164  568.72   170.8  569.33
     173  569.53     182   571.5   190.9  572.63   199.9  572.74   217.8  572.29
   227.6  572.16   247.1  572.17   305.5  572.51     325  572.93   334.8  573.32
   344.5  573.77   372.8  575.68   382.2  576.42     401   578.1   419.9     580
#Mann= 3 , 0 , 0
       0     .08       0   155.8    .045       0   170.8     .08       0
Bank Sta=155.8,170.8
XS Rating Curve= 0 ,0
Exp/Cntr=0.3,0.1

Type RM Length L Ch R = 1 ,1603.2  ,307.8,253.8,273.3
XS GIS Cut Line= 3
     1688075.136       585061.52     1688442.528       584942.02
     1688540.005      584972.937
#Sta/Elev= 30
       0     580     9.7   578.2    19.3  576.93      29   575.9    38.6  575.32
    48.3  575.17    67.6  575.69    77.3  575.75   125.6  574.96   154.5   573.8
   183.5  572.28   202.8  571.67   231.8  571.24   241.5   570.5   249.3  569.39
   251.1  569.13   260.8  568.84   270.4  569.96   280.1  571.41   289.8  572.24
   376.7  574.16   386.3  575.26   395.6  578.12   404.9  582.41   423.5  591.87
   442.1  601.08   451.4  605.48   460.7  609.55     470  613.17   488.6     620
#Mann= 3 , 0 , 0
       0     .08       0   249.3    .045       0   270.4     .08       0
#XS Ineff= 2 , 0
           78.17  576.07
Permanent Ineff=
       F       F
Bank Sta=249.3,270.4
XS Rating Curve= 0 ,0
Exp/Cntr=0.3,0.1

Type RM Length L Ch R = 1 ,1349.5  ,261.7,269.3,273.4
XS GIS Cut Line= 3
     1688082.166      585072.926     1688321.888      585112.241
     1688395.561      585175.238
#Sta/Elev= 24
       0  580.01    19.4  577.89    29.2   577.2    38.9  576.91    48.6  576.87
      68  577.05    77.7  576.96   116.6  575.74     136  575.01   174.9  573.86
   194.3  573.62   223.5  573.59   233.2   573.5   242.9   573.1   252.6  571.75
   262.3  569.52     272  568.45   281.7  569.84   291.4  573.12   301.1  578.29
   310.8  585.75   320.5  594.16   330.2  602.92   339.9     610
#Mann= 3 , 0 , 0
       0     .08       0   262.3    .045       0   281.7     .08       0
Bank Sta=262.3,281.7
XS Rating Curve= 0 ,0
Exp/Cntr=0.3,0.1

Type RM Length L Ch R = 1 ,1080.2  ,191.1,177.8,167.6
XS GIS Cut Line= 3
     1688055.571      585164.442     1688134.941       585297.74
      1688290.79      585406.007
#Sta/Elev= 30
       0  580.01     9.7  577.76    19.4  575.22    29.1  573.62    38.8  573.21
    87.3  572.26      97  571.94   106.7  571.43   116.4  569.88     126  567.61
   132.4  566.96   135.8  566.62   145.4  567.73   147.4   568.2   155.1     570
   174.1   572.4   183.6   575.5   193.1  579.95   212.1  589.62   221.6  594.34
     231  598.74   240.5  603.01     250  607.07   259.5  611.08     269  614.94
   278.5  618.59     288  621.98   297.5  625.21   316.4  631.23   344.9     640
#Mann= 3 , 0 , 0
       0     .08       0   132.4    .045       0   147.4     .08       0
Bank Sta=132.4,147.4
XS Rating Curve= 0 ,0
Exp/Cntr=0.3,0.1

Type RM Length L Ch R = 1 ,902.4   ,171.2,166.4,161.5
XS GIS Cut Line= 3
     1687760.332      585293.207      1688099.51      585455.996
     1688233.337      585484.747
#Sta/Elev= 30
       0     590    19.3  587.84    57.9  582.64    96.5  581.03   115.8  579.14
   125.4  577.41   144.7  572.81   154.4  571.38     164  570.64   173.6  570.64
   202.6  572.33   212.2  572.33   221.9  570.69   231.5  567.64   241.2  565.98
   250.8  565.83   257.4  566.07   260.5  566.18   272.4  568.18   279.8  569.62
   289.4  570.53   308.7  571.05   337.6  571.21   347.3  571.61   356.9  572.88
   366.6  575.89   376.2     580   425.1  601.93   483.8  626.95   513.1     640
#Mann= 3 , 0 , 0
       0     .08       0   257.4    .045       0   272.4     .08       0
#XS Ineff= 2 , 0
          208.73  574.43
Permanent Ineff=
       F       F
Bank Sta=257.4,272.4
XS Rating Curve= 0 ,0
Exp/Cntr=0.3,0.1

Type RM Length L Ch R = 1 ,736     ,395.6,391.4,385.9
XS GIS Cut Line= 3
     1687680.508      585445.377     1688095.458      585538.788
     1688158.999      585534.302
#Sta/Elev= 27
       0     580     9.7  577.22    19.3  574.71      29  573.39    48.3   572.5
      58  572.28    77.3  572.06   154.7  571.68     174  571.49   251.3  570.13
   309.3  569.36     348  568.58   357.7  568.11     366  566.98   367.3   566.8
     377  565.99     381  566.14   386.7  566.36   396.3  568.51     406  571.64
   415.7  575.43   425.3     580   443.5  589.37   452.6  593.85   461.7   598.1
   470.8  602.14     489     610
#Mann= 3 , 0 , 0
       0     .08       0     366    .045       0     381     .08       0
Bank Sta=366,381
XS Rating Curve= 0 ,0
Exp/Cntr=0.3,0.1

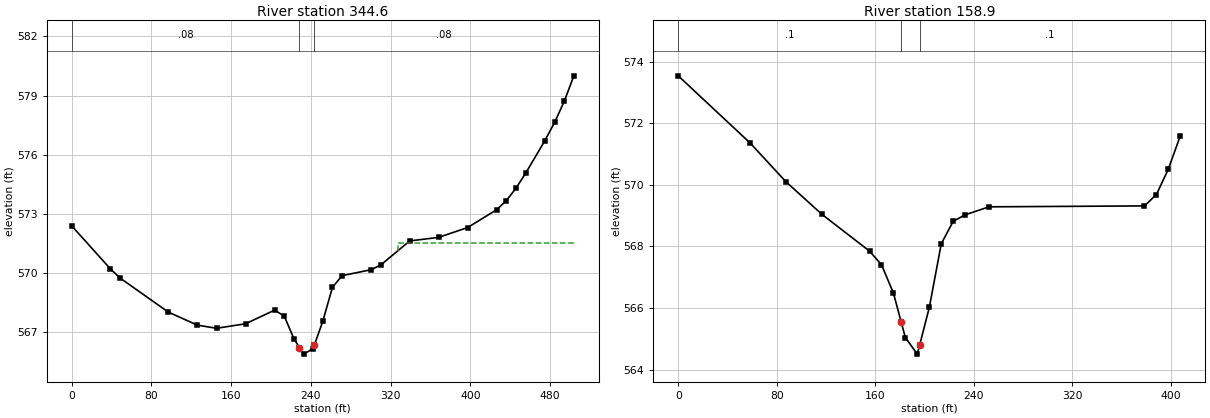
Type RM Length L Ch R = 1 ,344.6   ,192.9,185.7,178.3
XS GIS Cut Line= 2
     1687584.313      585809.863     1688086.597       585770.18
#Sta/Elev= 30
       0  572.39    38.8  570.21    48.4  569.75    96.9  568.02     126  567.36
   145.3   567.2   174.4  567.43   203.5  568.12   213.2  567.82   222.9  566.67
   228.5  566.22   232.6  565.89   242.2  566.17   243.5  566.36   251.9  567.56
   261.6  569.28   271.3  569.87   300.4  570.17   310.1  570.41   339.1  571.63
   368.2  571.81   397.3  572.31   426.3  573.21     436  573.67   445.7   574.3
   455.4  575.06   474.8  576.72   484.5  577.64   494.2  578.71   503.8     580
#Mann= 3 , 0 , 0
       0     .08       0   228.5    .045       0   243.5     .08       0
#XS Ineff= 2 , 0
                          327.04          571.54
Permanent Ineff=
       F       F
Bank Sta=228.5,243.5
XS Rating Curve= 0 ,0
Exp/Cntr=0.3,0.1

Type RM Length L Ch R = 1 ,158.9   ,156.9,158.9,160.9
XS GIS Cut Line= 2
     1687724.085      586024.343     1688102.672      585872.431
#Sta/Elev= 20
       0  573.55    58.3  571.37    87.4  570.11   116.6  569.05   155.4  567.85
   165.1  567.41   174.8  566.49   181.1  565.55   184.5  565.04   194.2   564.5
   196.1  564.79     204  566.02   213.7  568.09   223.4  568.82   233.1  569.03
   252.5  569.29   378.8  569.32   388.5  569.69   398.2  570.52   407.9   571.6
#Mann= 3 , 0 , 0
       0      .1       0   181.1    .045       0   196.1      .1       0
Bank Sta=181.1,196.1
XS Rating Curve= 0 ,0
Exp/Cntr=0.3,0.1

Chan Stop Cuts=-1
Use User Specified Reach Order=0
Composite Channel Slope=5